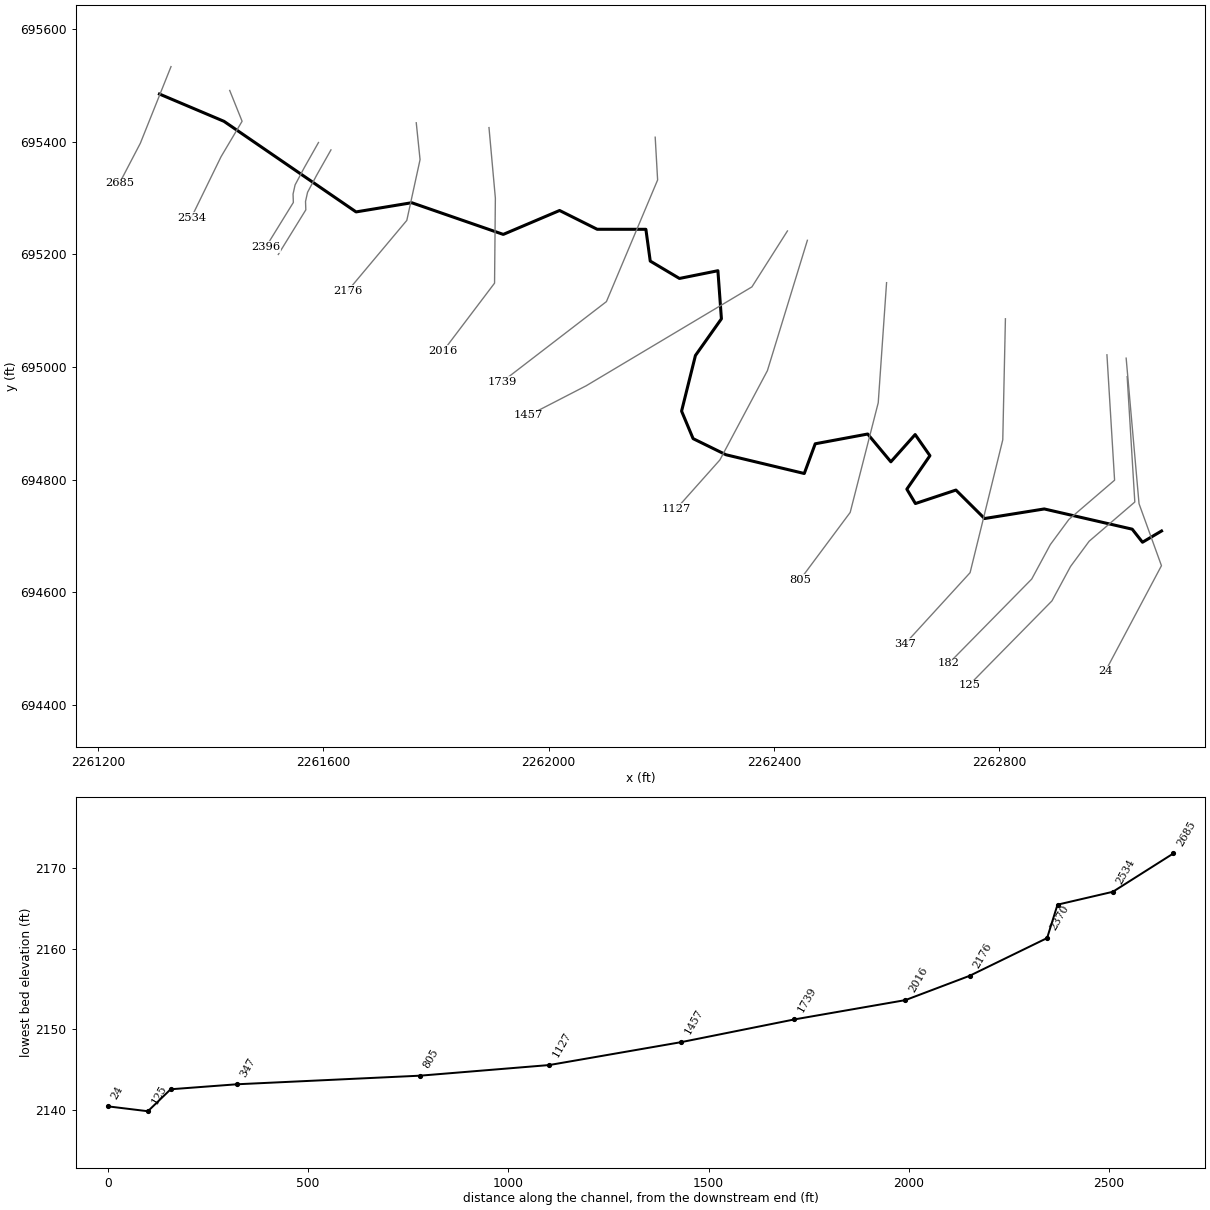
--- WHTESRN.prj (project) ---

Proj Title=WHTESRN
Current Plan=p01
Default Exp/Contr=0,0
English Units
Geom File=g01
Flow File=f01
Plan File=p01
BEGIN DESCRIPTION:
----------MODEL BY WOOD PLC 2022----------
AFH study
Randolph County, WV
HEC-RAS Version: RAS 6.2
Vertical Datum: NAVD88
Projection: NAD 1983 StatePlane West Virginia S FIPS 4702 (US Feet)
Terrain: 1-meter LIDAR (FEMA Region III 3DEP collected 2016-2018)
Land Use: 2019 NLCD
Hydrologic Method:
WV SIR2010-5033 regression equations
Additional Model Notes:
None
END DESCRIPTION:
DSS Export Rating Curves= 0
DSS Export Rating Curve Sorted= 0
DSS Export Volume Flow Curves= 0
DXF OffsetX= 0
DXF OffsetY= 0
DXF ScaleX= 0
DXF ScaleY= 0

--- WHTESRN.p01 (plan) ---

Plan Title=Floodplain
Program Version=6.20
Short Identifier=Floodplain
Geom File=g01
Flow File=f01
Subcritical Flow
K Sum by GR= 0
Std Step Tol= 0.01
Critical Tol= 0.01
Num of Std Step Trials= 20
Max Error Tol= 0.3
Flow Tol Ratio= 0.001
Split Flow NTrial= 30
Split Flow Tol= 0.02
Split Flow Ratio= 0.02
Log Output Level= 0
Friction Slope Method= 1
Unsteady Friction Slope Method= 2
Unsteady Bridges Friction Slope Method= 1
Parabolic Critical Depth
Global Vel Dist= 0 , 0 , 0
Global Log Level= 0
CheckData=True
Encroach Param=-1 ,0,0, 0
Mapping Interval=1HOUR
Computation Time Step Use Courant=        0
Computation Time Step Use Time Series=    0
Computation Time Step Count To Double=0
Computation Time Step Max Doubling=0
Computation Time Step Max Halving=0
Computation Time Step Residence Courant=0
Run HTab= 0
Run UNet= 0
Run Sediment= 0
Run PostProcess= 0
Run WQNet= 0
Run RASMapper=-1
UNET Theta= 0
UNET Theta Warmup= 0
UNET ZTol= 0
UNET ZSATol= 0
UNET MxIter= 0
UNET Max Iter WO Improvement= 0
UNET MaxInSteps= 0
UNET DtIC= 0
UNET DtMin= 0
UNET MaxCRTS= 0
UNET WFStab= 0
UNET SFStab= 0
UNET WFX= 1
UNET SFX= 1
UNET Gravity=32.174
UNET 1D Methodology=Finite Difference
UNET DSS MLevel= 1
UNET Pardiso=0
UNET DZMax Abort= 0
UNET Use Existing IB Tables= 0
UNET Froude Reduction=False
UNET Froude Limit= 0
UNET Froude Power= 0
UNET D1 Cores= 0
UNET WindReference=Eulerian
UNET WindDragFormulation=Hsu (1988)
UNET D2 Coriolis=0
UNET D2 Cores= 0
UNET D2 Theta= 1
UNET D2 Theta Warmup= 1
UNET D2 Z Tol= 0.01
UNET D2 Volume Tol= 0.01
UNET D2 Max Iterations= 20
UNET D2 Equation= 0
UNET D2 RampUpFraction=0.1
UNET D2 TimeSlices= 1
UNET D2 Turbulence Formulation=Non-Conservative (original)
UNET D2 Eddy Viscosity=0.3
UNET D2 Transverse Eddy Viscosity=0.1
UNET D2 Smagorinsky Mixing=0
UNET D2 BCVolumeCheck=0
UNET D2 Cores=0
UNET D2 SolverType=PARDISO (Direct)
UNET D2 Minimum Iterations= 2147483647
UNET D2 Maximum Iterations= 2147483647
UNET D2 Restart Number= 10
UNET D2 Relaxation Coeff=1.3
UNET D2 SOR Precondition Iterations= 10
UNET D2 ILUT Maximum Fill= 8
UNET D2 ILUT Tolerance=1E-08
UNET D1D2 MaxIter= 0
UNET D1D2 ZTol=0.01
UNET D1D2 QTol=0.1
UNET D1D2 MinQTol=1
Write IC File= 0
Write IC File at Fixed DateTime=0
Write IC File at Sim End=0
Echo Input=False
Echo Parameters=False
Echo Output=False
Write Detailed= 0
HDF Write Warmup=0
HDF Write Time Slices=0
HDF Flush=0
HDF Compression= 1
HDF Chunk Size= 1
HDF Spatial Parts= 1
HDF Use Max Rows=0
HDF Fixed Rows= 1
Calibration Method= 0
Calibration Iterations= 20
Calibration Max Change=0.05
Calibration Tolerance=0.2
Calibration Maximum=1.5
Calibration Minimum=0.5
Calibration Optimization Method= 1
WQ AD Non Conservative
WQ ULTIMATE=-1
WQ Max Comp Step=1HOUR
WQ Output Interval=15MIN
WQ Output Selected Increments= 0
WQ Output face flow=0
WQ Output face velocity=0
WQ Output face area=0
WQ Output face dispersion=0
WQ Output cell volume=0
WQ Output cell surface area=0
WQ Output cell continuity=0
WQ Output cumulative cell continuity=0
WQ Output face conc=0
WQ Output face dconc_dx=0
WQ Output face courant=0
WQ Output face peclet=0
WQ Output face adv mass=0
WQ Output face disp mass=0
WQ Output cell mass=0
WQ Output cell source sink temp=0
WQ Output nsm pathways=0
WQ Output nsm derived pathways=0
WQ Create Restart=0
WQ Fixed Restart=0
WQ System Summary=0
WQ Write To DSS=0
Sorting and Armoring Iterations= 10
XS Update Threshold= 0.02
Bed Roughness Predictor= 0
Hydraulics Update Threshold= 0.02
Energy Slope Method= 1
Volume Change Method= 1
Sediment Retention Method= 0
Sediment TS Multiplier= 1
Warm Up Method= 0
XS Weighting Method= 0
Number of US Weighted Cross Sections= 1
Number of DS Weighted Cross Sections= 1
Upstream XS Weight=0
Main XS Weight=1
Downstream XS Weight=0
Number of DS XS's Weighted with US Boundary= 1
Upstream Boundary Weight= 1
Weight of XSs Associated with US Boundary= 0
Number of US XS's Weighted with DS Boundary= 1
Downstream Boundary Weight= 0.5
Weight of XSs Associated with DS Boundary= 0.5
Percentile Method= 0
Sediment Output Level= 3
Mass or Volume Output= 0
Output Increment Type= 1
Profile and TS Output Increment= 1
Transport Output Increment 1
XS Output Flag= 0
XS Output Increment= 10
Read HDF5 Sediment Hotstart= 0
Sediment Hotstart Type= 0
Write Gradation File= 0
Read Gradation Hotstart= 0
Write HDF5 File= 1
Write Binary Output= 1
Write DSS Sediment File= 0
DSS Sediment Output Type= 1
SV Curve= 0
Specific Gage Flag= 0
Subcell Erosion Methods= 0
Subcell Deposition Methods= 0
Advection Scheme= 1
Matrix Solver= 0
Implicit Weighting Factor= 1
Maximum Outer Loop Convergence Iterations= 5
Convergence Maximum Absolute= 0.001
Convergence RMSE= 0.0001
Grain Fractions Max Abs Error= 0.001
Max Subgrid Regions= 1
Max Subgrid Length Scale= 3.402823E+38
Initial Layer Thickness= 3.402823E+38
Min Layer Thickness= 3.402823E+38
Max Layer Thickness= 3.402823E+38
Number of Layers= 5

--- WHTESRN.f01 (steady flow) ---

Flow Title=Flow
Program Version=6.20
Number of Profiles= 1
Profile Names=P100yr
River Rch & RM=WHTESRN,Main,2685
     349
Boundary for River Rch & Prof#=WHTESRN,Main            , 1
Up Type= 0
Dn Type= 3
Dn Slope=0.01395
DSS Import GetInterval= 0
DSS Import GetPeak= 0
DSS Import FillOption= 0

--- WHTESRN.g01 (geometry) ---

Geom Title=Geometry
Program Version=6.20

River Reach=WHTESRN         ,Main
Reach XY= 30
     2261309.074      695484.496     2261423.588      695436.073
     2261658.032      695275.2952261756.79726269695291.593491968
     2261919.317      695235.365     2262019.266      695277.811
     2262085.984      695244.4792262172.45570256695244.404261493
     2262180.198      695188.017     2262232.022      695157.178
     2262300.302      695170.894     2262306.522      695085.547
     2262260.413      695020.434     2262235.825      694921.688
     2262256.284      694872.842     2262314.718      694844.212
      2262453.61      694810.964      2262473.03      694863.704
     2262566.179       694881.03      2262607.29      694831.721
      2262650.42      694880.092     2262676.648      694842.584
     2262635.664      694783.158     2262650.884      694757.655
     2262722.804      694781.559      2262773.61      694731.049
     2262879.593      694748.0352263035.71523234694712.144882793
2263053.92829953694688.951680035      2263087.79      694708.938

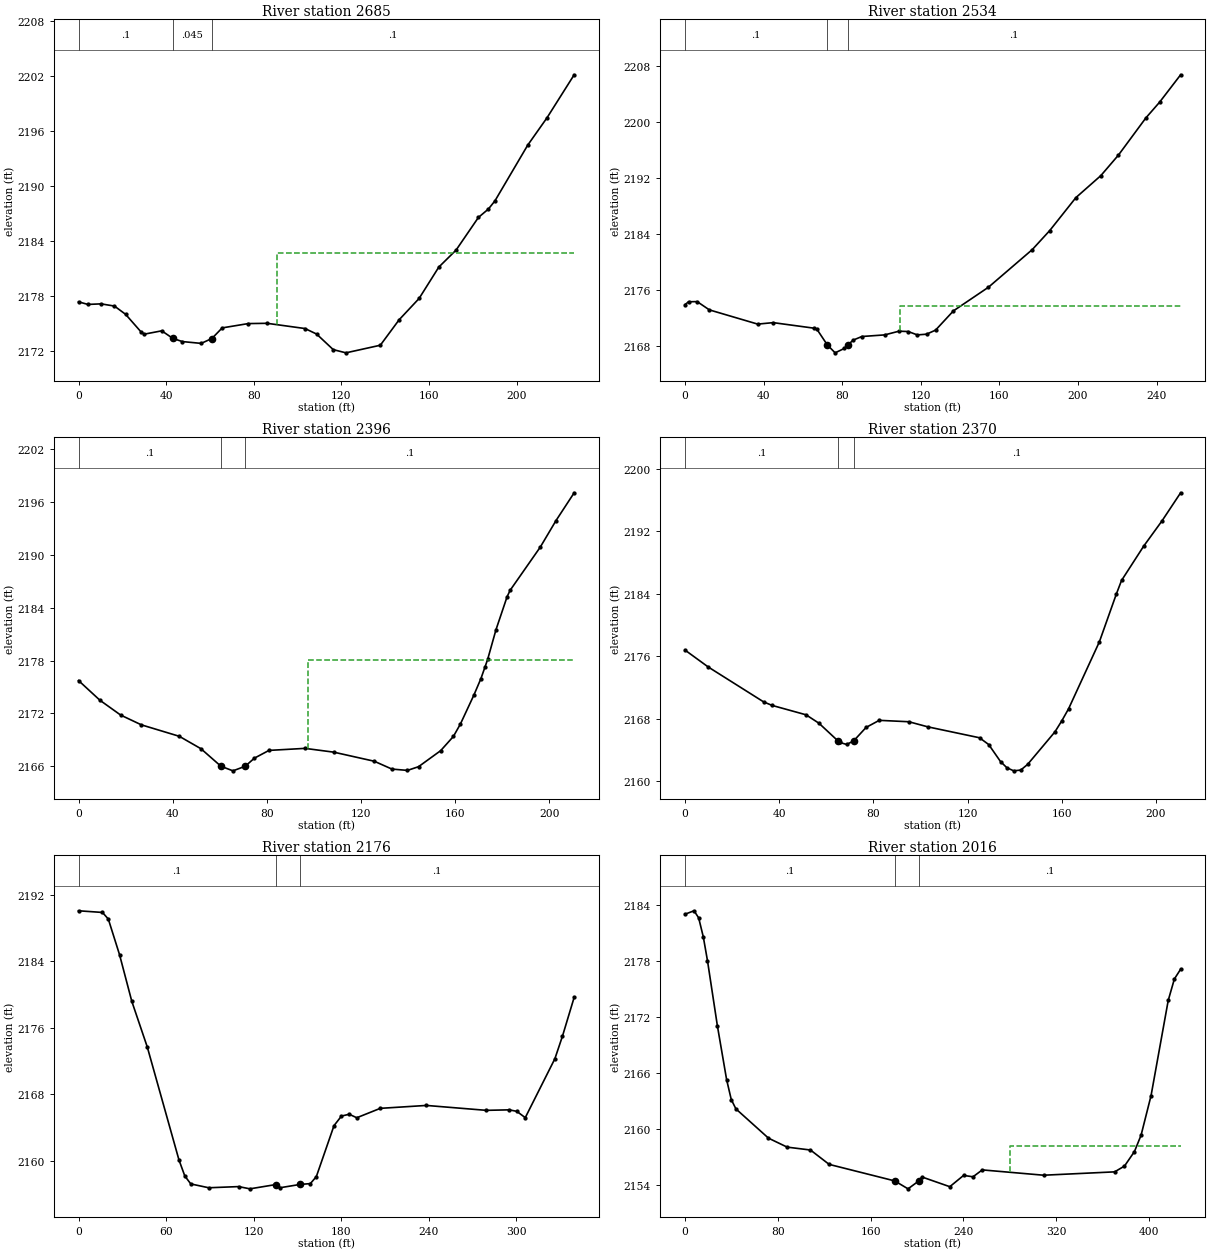
Type RM Length L Ch R = 1 ,2685    ,152.3,151.3,150.4
XS GIS Cut Line= 3
 2261329.5448155 695533.150908622261275.13824954695397.217076949
2261238.16257655 695326.43324961
#Sta/Elev= 30
       0 2177.41     4.3 2177.13    10.3 2177.19    16.4 2176.95    21.5 2176.05
    28.7 2174.09    30.1 2173.89      38 2174.25    43.1 2173.42    47.4 2173.08
      56 2172.88    60.92173.413    65.6 2174.57    77.5 2175.04    86.1 2175.07
   103.4  2174.5   108.7  2173.9   116.3  2172.2   122.1 2171.85   137.8 2172.68
   146.4 2175.46   155.5 2177.78   164.5  2181.2   172.4 2183.06   182.6 2186.62
   187.1 2187.52   190.1 2188.41   205.1  2194.5   213.9 2197.48   226.3 2202.17
#Mann= 3 ,-1,0
       0      .1       0    43.1    .045       0    60.9      .1       0
#XS Ineff= 2 , 0
                           90.61         2182.74
Permanent Ineff=
       F       F
Bank Sta=43.1,60.9
XS Rating Curve= 0 ,0
Exp/Cntr=0.3,0.1

Type RM Length L Ch R = 1 ,2534    ,137.8,138.1,138.2
XS GIS Cut Line= 4
2261433.75885221695490.838234373  2261455.727612695436.180942929
2261418.36865868695373.274915834 2261365.6932739 695265.29633914
#Sta/Elev= 30
       0 2173.95     1.8 2174.37     6.2 2174.39    12.4 2173.21      37 2171.18
    44.9 2171.39    65.9 2170.59    67.1 2170.46    72.4 2168.22    76.4 2167.08
      81  2167.7   82.862168.228    85.7 2168.91      90 2169.41   101.6 2169.64
   108.9 2170.17   113.6 2170.12   118.2 2169.64   122.9 2169.74   127.5 2170.32
   136.6 2173.07   154.4 2176.44   176.7 2181.81   185.6 2184.53   198.9 2189.23
   211.6 2192.37   220.5 2195.28   234.5  2200.6   241.5 2202.85   252.2 2206.76
#Mann= 3 ,-1,0
       0      .1       0    72.4    .045       0   82.86      .1       0
#XS Ineff= 2 , 0
                          109.19         2173.76
Permanent Ineff=
       F       F
Bank Sta=72.4,82.86
XS Rating Curve= 0 ,0
Exp/Cntr(USF)=0,0
Exp/Cntr=0.3,0.1

Type RM Length L Ch R = 1 ,2396    ,26.3,26,25.8
XS GIS Cut Line= 6
2261591.33323746695398.4705408672261566.32040628695354.247183018
2261549.77674147695323.1824830412261546.19023336695306.951922924
2261546.70389516695292.055730791 2261497.8698354695212.884960199
#Sta/Elev= 30
       0 2175.73     9.1 2173.49    17.9 2171.81    26.7  2170.7    42.8  2169.4
      52 2167.99   60.49    2166    65.6 2165.48    70.82166.002    74.7 2166.92
    80.9  2167.8    96.2 2168.03   108.4  2167.6   125.6 2166.57   133.1 2165.68
   139.7 2165.53   144.4 2165.95   153.8 2167.77   159.2 2169.38   162.2  2170.8
   167.9 2174.07   170.9 2175.95   172.6 2177.24   173.8 2178.17   177.3  2181.5
     182 2185.23   183.3 2185.97   196.1 2190.87   202.8 2193.89   210.5 2197.04
#Mann= 3 ,0,0
       0      .1       0   60.49    .045       0    70.8      .1       0
#XS Ineff= 2 , 0
                           97.27         2178.07
Permanent Ineff=
       F       F
Bank Sta=60.49,70.8
XS Rating Curve= 0 ,0
Exp/Cntr(USF)=0,0
Exp/Cntr=0.3,0.1

Type RM Length L Ch R = 1 ,2370    ,192,193.4,193.4
XS GIS Cut Line= 6
 2261613.4684063695385.3621829232261588.45557512695341.138825074
2261571.91191031695310.074125097 2261568.3254022 695293.84356498
  2261568.839064695278.9473728472261520.00500424695199.776602255
#Sta/Elev= 30
       0 2176.78     9.9 2174.61    33.4 2170.15      37  2169.7    51.4  2168.5
    56.9 2167.42   64.86 2165.19    65.8 2164.96    68.7  2164.7    71.7 2165.18
    76.9 2166.88    82.5 2167.79    95.1 2167.61   103.1 2166.96   125.1 2165.56
     129 2164.69     134 2162.52   136.7 2161.73   139.6 2161.33   142.6 2161.43
   145.5 2162.15   157.1 2166.31     160 2167.71   162.9 2169.26     176 2177.84
   183.2 2183.95   185.4 2185.68   194.8 2190.07   202.6 2193.31   210.5  2196.9
#Mann= 3 ,0,0
       0      .1       0   64.86    .045       0    71.7      .1       0
Bank Sta=64.86,71.7
XS Rating Curve= 0 ,0
Exp/Cntr(USF)=0,0
Exp/Cntr=0.3,0.1

Type RM Length L Ch R = 1 ,2176    ,158.6,160.3,163.4
XS GIS Cut Line= 4
2261764.86822975 695433.516911232261771.61728856695368.092523613
2261748.09121305695260.2212263682261643.17797606695135.056962684
#Sta/Elev= 30
       0 2190.08    16.4 2189.88    20.4 2189.09    28.1  2184.8    36.5 2179.19
    47.1  2173.7    68.8 2160.12    72.8 2158.19    76.9 2157.23    89.2 2156.77
   109.7 2156.91   117.4 2156.64     135 2157.15   138.3 2156.78   151.8 2157.17
   158.8 2157.27   162.9 2158.11     175 2164.24   180.1 2165.39   185.4 2165.61
   190.6 2165.19   206.7 2166.32   238.3 2166.67   279.3 2166.08     295 2166.14
   300.2 2165.96     306  2165.2   326.3 2172.29   331.5 2175.01   339.5 2179.67
#Mann= 3 ,-1,0
       0      .1       0     135    .045       0   151.8      .1       0
Bank Sta=135,151.8
XS Rating Curve= 0 ,0
Exp/Cntr=0.3,0.1

Type RM Length L Ch R = 1 ,2016    ,278.9,277.1,264.6
XS GIS Cut Line= 4
2261893.97477137 695424.929329662261905.28647084695299.797406676
2261903.85048182695148.8386788522261812.89359667 695028.65154359
#Sta/Elev= 30
       0 2183.05     7.8 2183.42    11.8 2182.66    15.8 2180.62    19.4 2178.07
    27.9 2171.12    35.9 2165.32    39.9 2163.19    43.9 2162.19      72 2159.05
    88.1 2158.09   108.2 2157.78   124.3 2156.24   180.8 2154.47   192.3 2153.62
  201.572154.467   204.3 2154.89   228.3 2153.85   240.2 2155.06   248.3 2154.91
   256.3 2155.65   309.2 2155.08   370.4 2155.44   378.9 2156.06   387.5 2157.62
   393.2 2159.37   401.8 2163.61   416.6 2173.81   421.9 2176.11   427.3 2177.16
#Mann= 3 ,-1,0
       0      .1       0   180.8    .045       0  201.57      .1       0
#XS Ineff= 2 , 0
                          280.02         2158.19
Permanent Ineff=
       F       F
Bank Sta=180.8,201.57
XS Rating Curve= 0 ,0
Exp/Cntr(USF)=0,0
Exp/Cntr=0.3,0.1

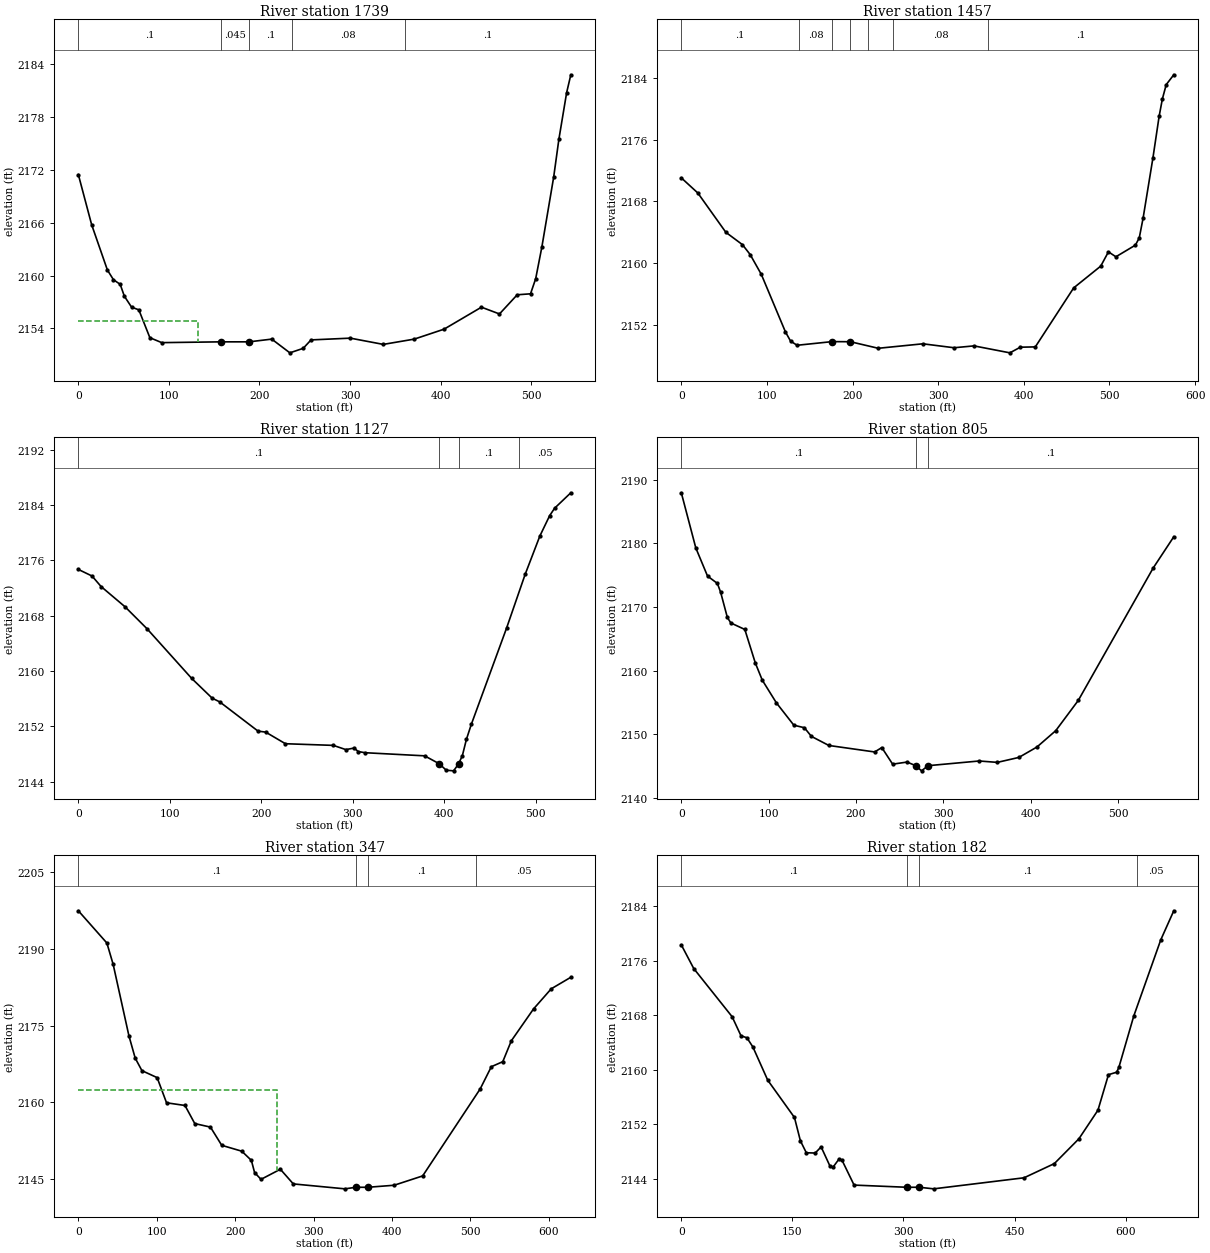
Type RM Length L Ch R = 1 ,1739    ,280.6,282.2,247.8
XS GIS Cut Line= 4
2262188.98838274695407.8943295262262193.29338108695332.003844795
2262102.42257524695116.0675723532261917.23591512 694973.70319507
#Sta/Elev= 30
       0 2171.48    14.7 2165.78    32.1 2160.63    38.8 2159.53    46.2 2159.01
    50.8 2157.66    58.8 2156.41    66.8 2156.11      79 2152.94    92.1 2152.38
   157.2 2152.47  188.582152.471   213.6 2152.78   233.6 2151.22   248.3 2151.73
     257 2152.69   300.4 2152.89   336.8 2152.18     371 2152.78   403.9 2153.91
   445.2 2156.41   465.1 2155.64   484.7 2157.82   499.4 2157.93   505.1 2159.65
   511.9 2163.24     525 2171.22   530.7 2175.49   539.3 2180.81   543.9 2182.83
#Mann= 5 ,-1,0
       0      .1       0   157.2    .045       0  188.58      .1       0
  236.01     .08       0  360.29      .1       0
#XS Ineff= 2 , 0
          131.89 2154.85
Permanent Ineff=
       F       F
Bank Sta=157.2,188.58
XS Rating Curve= 0 ,0
Exp/Cntr=0.3,0.1

Type RM Length L Ch R = 1 ,1457    ,312.4,329.8,322.9
XS GIS Cut Line= 4
2262423.71515192695241.480422595 2262360.6654661695142.195796923
2262066.53529816694966.7109254122261964.36205587694914.044305671
#Sta/Elev= 30
       0 2171.06    19.3  2169.1      52 2164.01    71.4 2162.41    80.4 2161.13
    93.4 2158.57   121.6 2151.11   127.6 2149.92   135.2 2149.38  176.182149.853
   197.4 2149.84     230 2148.99   282.1 2149.57   318.5 2149.06   341.8  2149.3
   383.7  2148.4   395.9 2149.13   413.4 2149.17   458.2 2156.81   489.8 2159.63
   498.8 2161.48   507.5 2160.84   530.3 2162.35   534.8 2163.29   539.3 2165.86
   550.8 2173.68     558 2179.04   561.8 2181.29   566.3 2183.14   575.1 2184.41
#Mann= 7 ,-1,0
       0      .1       0  137.61     .08       0  176.18    .045       0
   197.4     .08       0  217.61      .1       0  247.61     .08       0
  357.61      .1       0
Bank Sta=176.18,197.4
XS Rating Curve= 0 ,0
Exp/Cntr(USF)=0,0
Exp/Cntr=0.3,0.1

Type RM Length L Ch R = 1 ,1127    ,309,322.1,318.5
XS GIS Cut Line= 4
2262459.12141622695224.9174252072262388.12466034694993.438001202
2262303.84719457694835.0744074862262226.20838073694747.929151317
#Sta/Elev= 30
       0 2174.67      15 2173.71    24.8  2172.2      51 2169.27      75  2166.1
   123.8 2158.92   146.2 2156.06   154.5 2155.52   196.4 2151.29   204.7 2151.15
   226.3 2149.47   278.7 2149.23   292.3 2148.62   301.3 2148.84   305.9 2148.34
   313.3 2148.17   378.4 2147.72  394.472146.572     402 2145.64   410.1 2145.55
  415.562146.556   419.7 2147.76   424.1  2150.1   429.4 2152.25     468 2166.19
   488.3 2173.96   504.4 2179.51   515.1 2182.45   520.5 2183.52   538.2 2185.75
#Mann= 4 ,-1,0
       0      .1       0  394.47    .045       0  415.56      .1       0
  481.52     .05       0
Bank Sta=394.47,415.56
XS Rating Curve= 0 ,0
Exp/Cntr=0.3,0.1

Type RM Length L Ch R = 1 ,805     ,455.1,457.6,447.8
XS GIS Cut Line= 4
2262599.67632889695149.7057061422262584.88169022694936.542829409
2262535.09066792694741.8554028812262446.06184354694622.285790903
#Sta/Elev= 30
       0 2187.97    16.6 2179.29      30 2174.87    41.3 2173.71      45 2172.33
    52.7 2168.36    56.7 2167.49    72.7 2166.47    84.7  2161.2    92.7 2158.49
   108.8 2154.93   128.8 2151.41   140.9 2151.01   148.9 2149.65   168.9 2148.22
   221.3  2147.2   229.5 2147.89   241.9 2145.28   258.4 2145.61  268.342145.043
     275 2144.23  282.35 2145.04     341 2145.78   361.7 2145.56   386.4 2146.34
   407.1 2147.98   428.6 2150.55   454.4 2155.31   540.1 2176.13   563.7 2181.05
#Mann= 3 ,-1,0
       0      .1       0  268.34    .045       0  282.35      .1       0
Bank Sta=268.34,282.35
XS Rating Curve= 0 ,0
Exp/Cntr(USF)=0,0
Exp/Cntr=0.3,0.1

Type RM Length L Ch R = 1 ,347     ,173.2,165.4,164.8
XS GIS Cut Line= 4
2262810.63537817695085.6147043852262805.94118574694870.775642042
2262747.91615285694634.8973849092262632.91262844694509.099443044
#Sta/Elev= 30
       0 2197.39    36.4  2191.1    44.4 2186.94    64.5 2173.01    72.5 2168.66
    81.1 2166.21   100.5 2164.85   112.5 2159.94     136 2159.42   148.5 2155.89
   168.5  2155.2   182.9 2151.65   208.5  2150.5   220.7 2148.71   224.8 2146.34
     233 2145.01   257.7 2146.98   274.2 2144.12     340 2143.16  354.282143.467
   368.9 2143.46   402.8 2143.86   439.2 2145.68   512.6 2162.65   526.8 2166.98
   541.4 2167.96   552.3 2172.03   580.6 2178.24   603.2 2182.17   628.2 2184.42
#Mann= 4 ,-1,0
       0      .1       0  354.28    .045       0   368.9      .1       0
   507.8     .05       0
#XS Ineff= 2 , 0
          253.72 2162.46
Permanent Ineff=
       F       F
Bank Sta=354.28,368.9
XS Rating Curve= 0 ,0
Exp/Cntr(USF)=0,0
Exp/Cntr=0.3,0.1

Type RM Length L Ch R = 1 ,182     ,55.9,56.8,56.8
XS GIS Cut Line= 6
2262990.84012474695021.6532635882263004.41099737694799.112939436
2262923.34777835694729.4801352612262890.29309168694684.672671109
2262857.30142694694623.5711824012262710.32996051694474.186872924
#Sta/Elev= 30
       0 2178.31    16.8 2174.84    68.6 2167.78    80.6 2164.98    88.6 2164.69
    96.7 2163.33   116.7 2158.47   152.8    2153   160.8 2149.58   168.8 2147.83
   180.8 2147.79   188.8 2148.69   200.8 2145.86   204.9 2145.72   212.9  2146.9
   216.9 2146.76   233.3 2143.09   304.4 2142.77   321.4 2142.77   340.8 2142.54
   462.8 2144.16   503.7 2146.24   536.9 2149.88   562.6 2154.07   576.8 2159.28
   587.9 2159.64   590.9 2160.37     611 2167.89   647.4 2179.04     665 2183.31
#Mann= 4 ,-1,0
       0      .1       0   304.4    .045       0   321.4      .1       0
  615.44     .05       0
Bank Sta=304.4,321.4
XS Rating Curve= 0 ,0
Exp/Cntr(USF)=0,0
Exp/Cntr=0.3,0.1

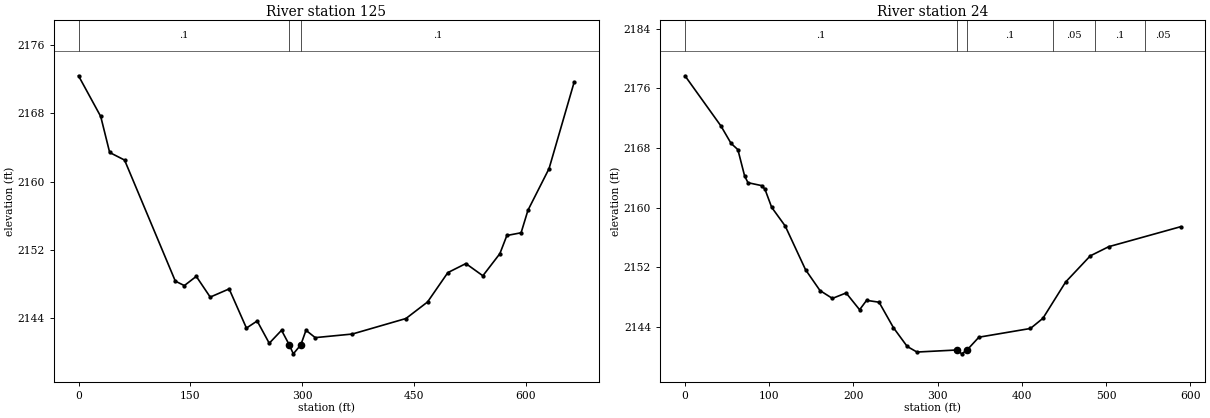
Type RM Length L Ch R = 1 ,125     ,89.8,100.5,104.8
XS GIS Cut Line= 6
2263026.74541643 694982.886516292263040.31628905694760.346192138
2262959.25307003694690.7133879632262926.19838336694645.905923811
2262893.20671862694584.8044351042262746.23525219694435.420125626
#Sta/Elev= 30
       0  2172.4    29.8 2167.63    41.8 2163.41    61.8 2162.52   129.9 2148.33
     142 2147.81     158 2148.89   176.7 2146.46   202.1 2147.42   225.3 2142.83
   239.7 2143.66   255.9 2141.05   272.4 2142.57   282.6 2140.89   288.2 2139.81
  298.272140.866   305.2 2142.57   317.6 2141.71   367.3 2142.13   439.3 2143.95
   468.3 2145.89   495.5 2149.33   519.7 2150.39   542.5 2148.96   565.3 2151.55
   574.7 2153.68   593.8    2154     603 2156.64   631.3 2161.52     665 2171.66
#Mann= 3 ,-1,0
       0      .1       0   282.6    .045       0  298.27      .1       0
Bank Sta=282.6,298.27
XS Rating Curve= 0 ,0
Exp/Cntr(USF)=0,0
Exp/Cntr=0.3,0.1

Type RM Length L Ch R = 1 ,24      ,,,
XS GIS Cut Line= 4
2263024.93794629695015.7104922092263047.80930369 694757.34444094
2263087.60186083694647.3297241512262988.12046799694460.070631745
#Sta/Elev= 30
       0 2177.69    42.7 2170.96    54.7 2168.63    62.8 2167.79    70.8 2164.26
    74.8 2163.36    90.9 2162.97    94.9  2162.5   102.9 2160.06     119 2157.55
   143.1  2151.7   160.3  2148.9     175 2147.85   191.3 2148.58   207.3 2146.33
   215.6 2147.59   230.4 2147.34   247.5 2143.92   263.8 2141.41   275.4 2140.66
   323.4 2140.94   328.5 2140.42   334.8 2140.93   348.9 2142.65   410.1 2143.82
   424.9 2145.18   451.9 2150.05   481.1 2153.55     503 2154.78   588.4 2157.46
#Mann= 6 ,-1,0
       0      .1       0   323.4    .045       0   334.8      .1       0
  436.37     .05       0  486.37      .1       0  546.37     .05       0
Bank Sta=323.4,334.8
XS Rating Curve= 0 ,0
Exp/Cntr(USF)=0,0
Exp/Cntr=0.3,0.1
LCMann Table=0

Chan Stop Cuts=-1
Use User Specified Reach Order=0
Composite Channel Slope=5